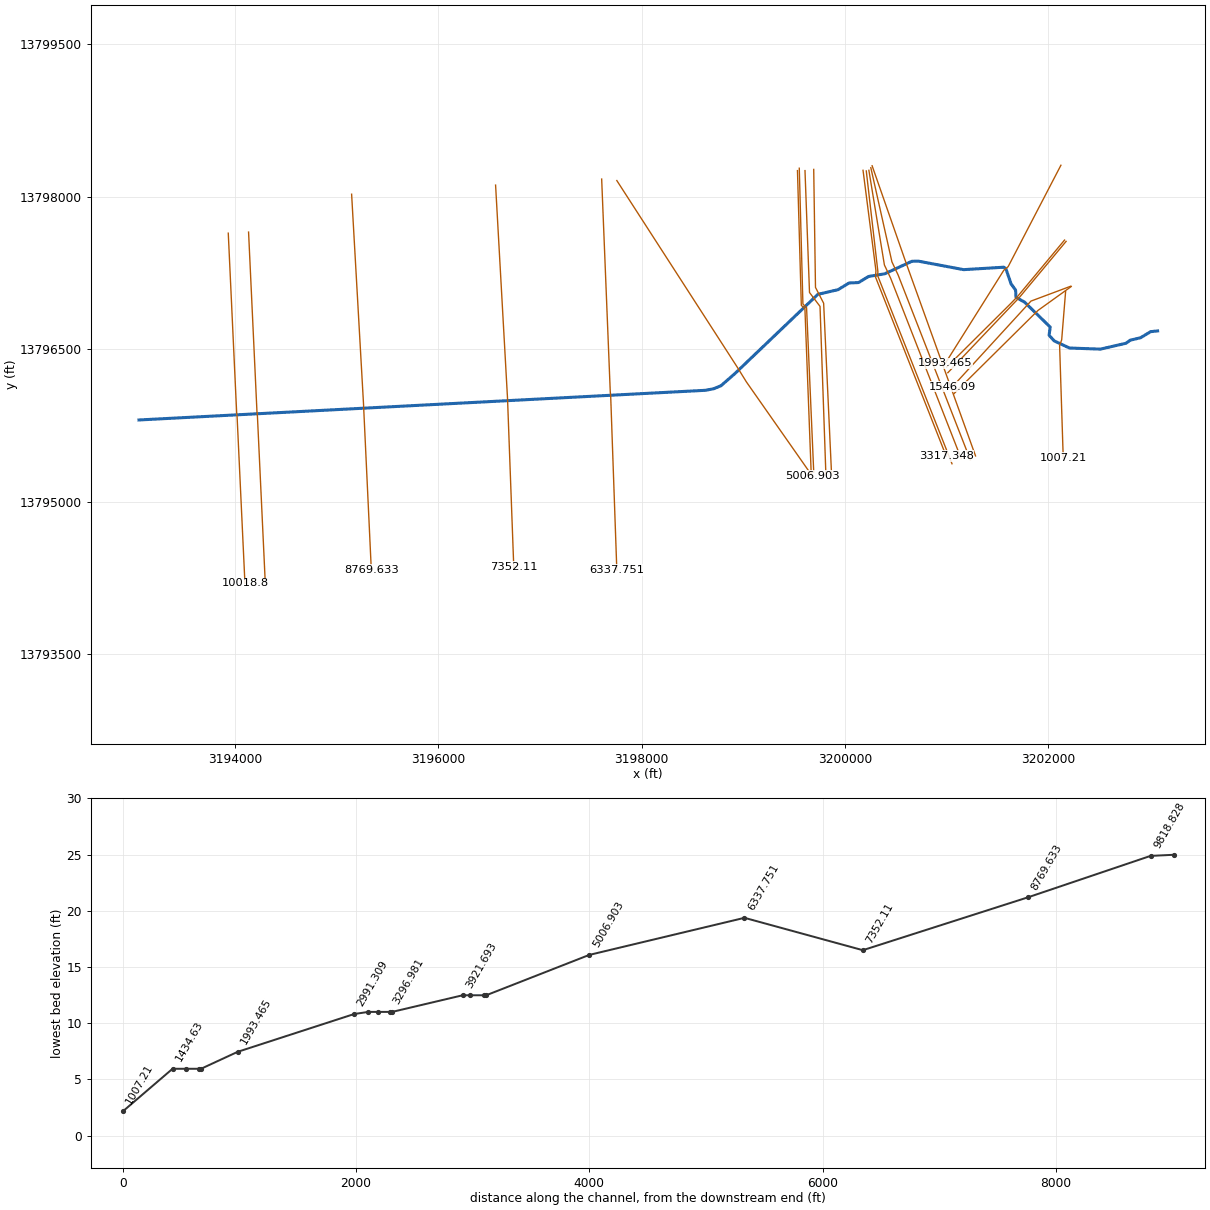
--- B111-00-00_Updated.prj (project) ---

Proj Title=B111-00-00
Current Plan=p05
Default Exp/Contr=.3,.1
English Units
Geom File=g04
Flow File=f03
Flow File=f04
Plan File=p05
Plan File=p06
Y Axis Title=Elevation
X Axis Title(PF)=Main Channel Distance
X Axis Title(XS)=Station
BEGIN DESCRIPTION:
Armand Bayou
Armand Bayou 9.39
HCFCD Unit B111-00-00
Flood Hazard Model
10, 2, 1, 0.2% Event
Filename B111_00_00.prj
Prepared by: Christopher Moss Date: 6/15/2004
Reviewd by:		Date:
Status FINAL
END DESCRIPTION:
DSS Export Rating Curves= 0
DSS Export Rating Curve Sorted= 0
DSS Export Volume Flow Curves= 0
DXF OffsetX= 0
DXF OffsetY= 0
DXF ScaleX= 1
DXF ScaleY= 10

--- B111-00-00_Updated.p05 (plan) ---

Plan Title=FEMA Effective MP
Version=Version 3.0.1  Mar 2001
Short Identifier=Eff+LOMR MP
Geom File=g04
Flow File=f03
Subcritical Flow
K Sum by GR= 0
Std Step Tol= 0.01
Critical Tol= 0.01
Num of Std Step Trials= 20
Max Error Tol= 0.3
Flow Tol Ratio= 0.001
Split Flow NTrial= 30
Split Flow Tol= 0.02
Split Flow Ratio= 0.02
Log Output Level= 0
Friction Slope Method= 0
Unsteady Friction Slope Method= 2
Secant Critical Depth
Global Vel Dist= 0 , 0 , 0
Global Log Level= 0
CheckData=True
Encroach Param=-1 ,0,0, 0
BEGIN DESCRIPTION:
FEMA Effective June 2007 + LOMR 09-06-3048P + LOMR 10-06-2360X
END DESCRIPTION:
Computation Interval=1HOUR
Output Interval=1HOUR
Run HTab= 0
Run UNet= 0
Run PostProcess= 0
UNET Theta= 1
UNET ZTol= 0.02
UNET ZSATol= 0.1
UNET MxIter= 20
UNET MaxInSteps= 20
UNET DtIC= 0
UNET DtMin= 0
UNET MaxCRTS= 20
UNET WFStab= 2
UNET SFStab= 1
UNET WFX= 1
UNET SFX= 1
UNET Convert EG Bridges=-1
UNET Use Existing IB Tables=-1
Instantaneous Interval=1HOUR
Write IC File= 0
Write Velocity= 0
Write Detailed= 0

--- B111-00-00_Updated.p06 (plan) ---

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Plan Title=FEMA Effective FW
Short Identifier=Eff+LOMR FW
Geom File=g04
Flow File=f04
Encroach Param=-1 ,0,0, 2
Encroach River=B111-00-00
Encroach Reach=B111-00-00_0007
Encroach Node=10018.8
       1 4972.42 5017.58
Encroach Node=9818.828
       1 4972.42 5017.58
Encroach Node=8769.633
       1 4977.43 5022.57
Encroach Node=7352.11
       1 4977.43 5022.57
Encroach Node=6337.751
       1 4977.45 5022.55
Encroach Node=5006.903
       1  4974.8 5025.19
Encroach Node=4123.376
       1    4775    5225
Encroach Node=4103.376
       1    4775    5225
Encroach Node=4045.5
       1    4775    5225
Encroach Node=3987.452
       1    4775    5225
Encroach Node=3921.693
       1    4775    5225
Encroach Node=3317.348
       1    4900    5100
Encroach Node=3296.981
       1    4900    5100
Encroach Node=3245.9
       1    4900    5100
Encroach Node=3192.785
       1    4920    5080
Encroach Node=3112.617
       1    4950    5050
Encroach Node=2991.309
       1    4970    5030
Encroach Node=1993.465
       1 4968.04 5021.96
Encroach Node=1678.828
       1  4984.6    5052
Encroach Node=1658.57
       1  4954.6  5045.4
Encroach Node=1602.3
       1  4954.6  5045.4
Encroach Node=1546.09
       1  4969.6    5077
Encroach Node=1434.63
       1    4963    5134
Encroach Node=1007.21
       1 4982.63 5030.56
Encroach Node=966.799
       1 4985.12 5014.88
Encroach Node=893.7
       1 4985.12 5014.88
Encroach Node=820.671
       1 4985.12 5014.88
Encroach Node=659.977
       1  4979.3    5019

--- B111-00-00_Updated.f03 (steady flow) ---

Flow Title=FEMA Effective
Version=Version 3.0.1  Mar 2001
Number of Profiles= 4
Profile Names=10PCT_10yr, 2PCT_50yr, 1PCT_100yr, 0.2PCT_500yr
River Rch & RM=B111-00-00,B111-00-00_0007 ,10018.8
      69     101     118     165
River Rch & RM=B111-00-00,B111-00-00_0007 ,9818.828
      69     101     118     165
River Rch & RM=B111-00-00,B111-00-00_0007 ,8769.633
     111     163     191     268
River Rch & RM=B111-00-00,B111-00-00_0007 ,7352.11
     157     231     269     378
River Rch & RM=B111-00-00,B111-00-00_0007 ,6337.751
     246     362     423     594
River Rch & RM=B111-00-00,B111-00-00_0007 ,5006.903
     333     489     571     802
River Rch & RM=B111-00-00,B111-00-00_0007 ,4123.376
     515     756     882    1238
River Rch & RM=B111-00-00,B111-00-00_0007 ,3921.693
     555     813     947    1330
River Rch & RM=B111-00-00,B111-00-00_0007 ,3317.348
     577     846     985    1382
River Rch & RM=B111-00-00,B111-00-00_0007 ,2991.309
     653     955    1110    1555
River Rch & RM=B111-00-00,B111-00-00_0007 ,1993.465
     679     992    1152    1614
River Rch & RM=B111-00-00,B111-00-00_0007 ,1678.828
     700    1022    1186    1661
River Rch & RM=B111-00-00,B111-00-00_0007 ,1434.63
     738    1077    1248    1747
River Rch & RM=B111-00-00,B111-00-00_0007 ,1007.21
     755    1101    1276    1786
River Rch & RM=B111-00-00,B111-00-00_0007 ,820.671
     771    1123    1301    1821
Boundary for River Rch & Prof#=B111-00-00,B111-00-00_0007 , 1
Up Type= 0
Dn Type= 3
Dn Slope=.0025
DSS Import GetInterval= 0
DSS Import GetPeak= 0
DSS Import FillOption= 0

--- B111-00-00_Updated.f04 (steady flow) ---

Flow Title=Floodway
Version=Version 3.0.1  Mar 2001
Number of Profiles= 2
Profile Names=1PCT_100yr, 1PCTFloodway_100yrFW
River Rch & RM=B111-00-00,B111-00-00_0007 ,10018.8
     118     118
River Rch & RM=B111-00-00,B111-00-00_0007 ,9818.828
     118     118
River Rch & RM=B111-00-00,B111-00-00_0007 ,8769.633
     191     191
River Rch & RM=B111-00-00,B111-00-00_0007 ,7352.11
     269     269
River Rch & RM=B111-00-00,B111-00-00_0007 ,6337.751
     423     423
River Rch & RM=B111-00-00,B111-00-00_0007 ,5006.903
     571     571
River Rch & RM=B111-00-00,B111-00-00_0007 ,4123.376
     882     882
River Rch & RM=B111-00-00,B111-00-00_0007 ,3921.693
     947     947
River Rch & RM=B111-00-00,B111-00-00_0007 ,3317.348
     985     985
River Rch & RM=B111-00-00,B111-00-00_0007 ,2991.309
    1110    1110
River Rch & RM=B111-00-00,B111-00-00_0007 ,1993.465
    1152    1152
River Rch & RM=B111-00-00,B111-00-00_0007 ,1678.828
    1186    1186
River Rch & RM=B111-00-00,B111-00-00_0007 ,1434.63
    1248    1248
River Rch & RM=B111-00-00,B111-00-00_0007 ,1007.21
    1276    1276
River Rch & RM=B111-00-00,B111-00-00_0007 ,820.671
    1301    1301
Boundary for River Rch & Prof#=B111-00-00,B111-00-00_0007 , 1
Up Type= 0
Dn Type= 3
Dn Slope=.0025
DSS Import GetInterval= 0
DSS Import GetPeak= 0
DSS Import FillOption= 0

--- B111-00-00_Updated.g04 (geometry) ---

Geom Title=B111-00-00
Version=Version 3.0.1  Mar 2001

River Reach=B111-00-00      ,B111-00-00_0007
Reach XY= 30
     3193053.934    13795805.216      3198626.25       13796097.
        3198707.       13796112.      3198779.75       13796142.
        3198914.       13796259.      3199732.75       13797041.
       3199931.5       13797087.      3200040.25       13797153.
        3200133.       13797157.       3200231.5       13797217.
        3200390.       13797243.      3200657.25       13797366.
        3200720.       13797368.        3201167.       13797284.
      3201562.25       13797308.      3201581.75       13797296.
        3201633.       13797145.      3201678.25       13797082.
      3201682.25       13797010.      3201764.75       13796966.
      3202018.75       13796719.       3202007.5       13796639.
        3202058.       13796583.      3202208.25       13796513.
      3202512.75       13796502.       3202764.5       13796560.
      3202805.75       13796590.      3202907.25       13796614.
        3203007.       13796674.      3203075.25       13796681.

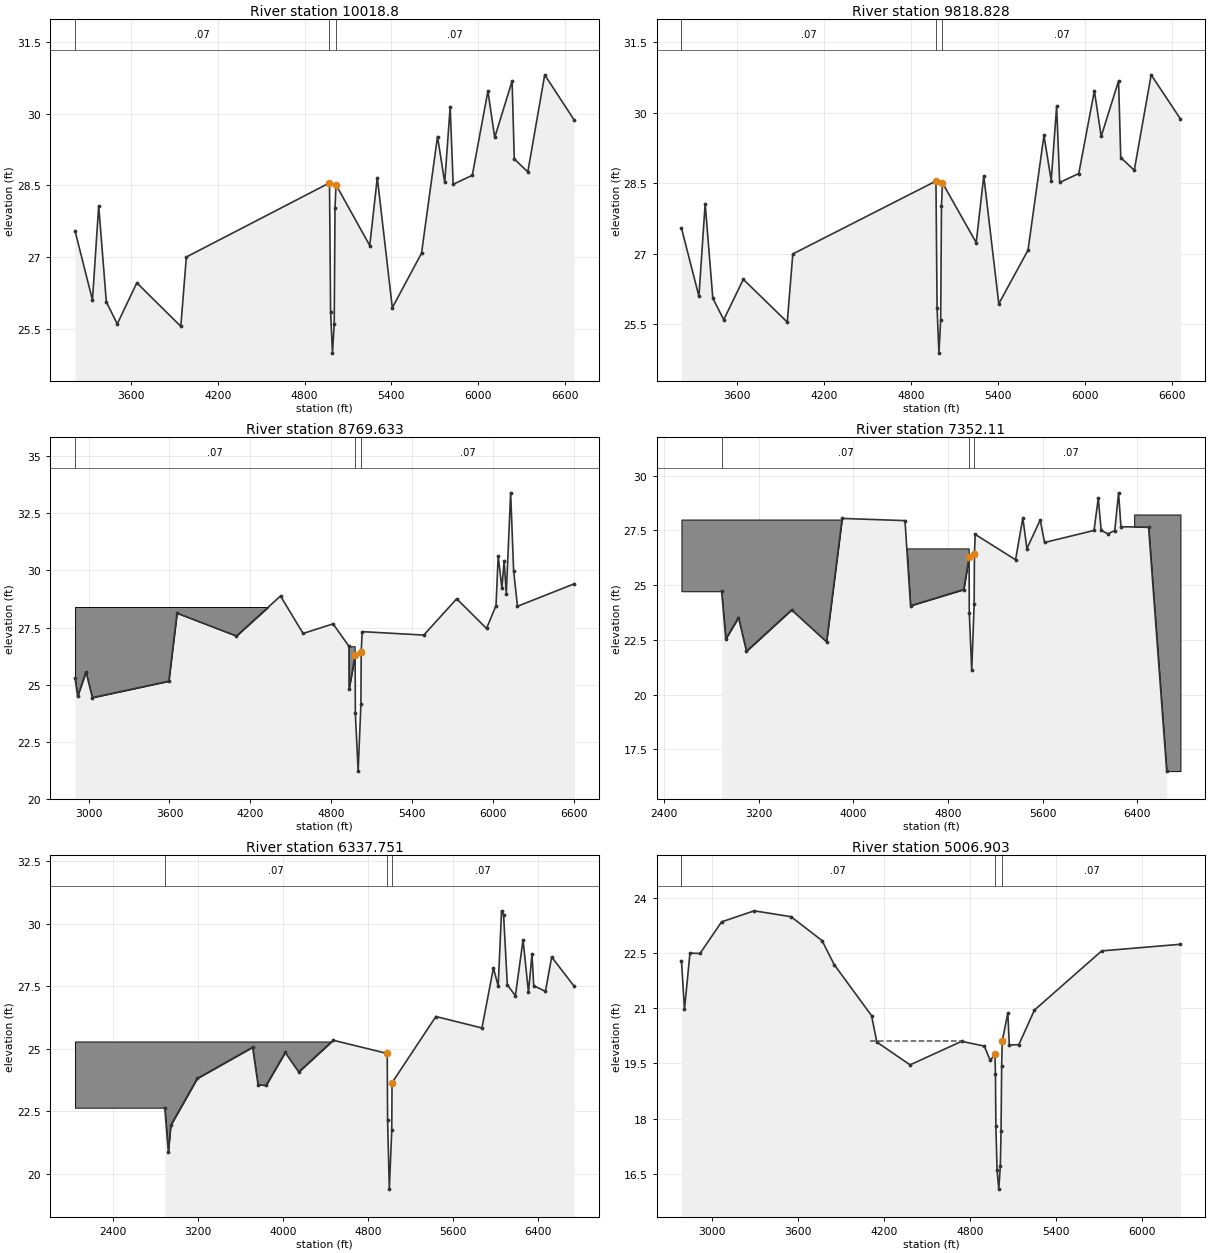
Type RM Length L Ch R = 1 ,10018.8 ,200,200,200
BEGIN DESCRIPTION:
CROSS SECTION COPIED FROM DOWNSTREAM SECTION TO MODEL UPSTREAM LIMIT OF CHANNEL AT SPACE CENTER BOULEVARD
END DESCRIPTION:
XS GIS Cut Line= 4
      3193932.43      13797642.8     3194014.737     13795881.63
     3194019.383     13795836.71     3194096.429     13794198.83
#Sta/Elev= 30
 3213.97   27.55 3334.71    26.1 3377.75   28.07 3430.58   26.06 3506.03    25.6
 3641.18   26.46 3945.13   25.55 3983.34      27 4972.42   28.55 4980.22   25.84
 4993.08   24.99 5005.17    25.6 5010.66   28.03 5017.58   28.51 5250.58   27.24
 5302.86   28.66 5406.56   25.94 5608.52   27.08 5718.76   29.52 5768.73   28.56
 5806.29   30.14 5827.15   28.52 5959.28   28.71 6067.04   30.47 6114.11    29.5
 6234.24   30.68 6249.26   29.05 6342.76   28.78 6459.53   30.81 6661.91   29.87
#Mann= 3 ,-1 , 0
 3213.97     .07       0 4972.42    .032       0 5017.58     .07       0
#Block Obstruct= 2 , 0
         4900.13   28.64 5035.09           28.39
Bank Sta=4972.42,5017.58
XS Rating Curve= 0
Exp/Cntr=.3,.1

Type RM Length L Ch R = 1 ,9818.828,1050.14,1049.19,1048.05
XS GIS Cut Line= 4
      3194132.14    13797653.527     3194214.449    13795892.359
     3194219.095    13795847.441     3194296.141     13794209.56
#Sta/Elev= 30
 3213.97   27.55 3334.71    26.1 3377.75   28.07 3430.58   26.06 3506.03    25.6
 3641.18   26.46 3945.13   25.55 3983.34      27 4972.42   28.55 4980.22   25.84
 4993.08   24.89 5005.17    25.6 5010.66   28.03 5017.58   28.51 5250.58   27.24
 5302.86   28.66 5406.56   25.94 5608.52   27.08 5718.76   29.52 5768.73   28.56
 5806.29   30.14 5827.15   28.52 5959.28   28.71 6067.04   30.47 6114.11    29.5
 6234.24   30.68 6249.26   29.05 6342.76   28.78 6459.53   30.81 6661.91   29.87
#Mann= 3 ,-1 , 0
 3213.97     .07       0 4972.42    .032       0 5017.58     .07       0
#Block Obstruct= 2 , 0
         4900.13   28.64 5035.09           28.39
Bank Sta=4972.42,5017.58
XS Rating Curve= 0
Exp/Cntr=.3,.1

Type RM Length L Ch R = 1 ,8769.633,1417.61,1417.52,1416.7
XS GIS Cut Line= 4
     3195145.952     13798026.25      3195263.73    13795950.144
     3195265.397    13795908.023     3195339.768    13794328.831
#Sta/Elev= 30
 2898.81    25.3  2918.3   24.49 2979.99   25.56 3027.63   24.43 3594.92   25.15
 3655.79   28.13 4096.68   27.13 4423.71   28.88 4591.46   27.24 4813.74   27.66
 4931.65   26.68 4932.09    24.8 4977.43   26.28 4979.09   23.74 4999.71   21.21
 5020.24   24.13 5022.57   26.44 5029.44   27.32 5486.93   27.17 5731.02   28.76
 5952.31   27.46 6022.79   28.46 6038.67   30.63  6066.5   29.24 6082.85   30.42
 6098.85   28.99 6131.41    33.4  6153.4   29.99 6181.93   28.43 6601.35   29.41
#Mann= 3 ,-1 , 0
 2898.81     .07       0 4977.43    .032       0 5022.57     .07       0
#Block Obstruct= 2 ,-1
 2898.81 4406.88    28.4 4919.54 4973.87   26.68
Bank Sta=4977.43,5022.57
XS Rating Curve= 0
Exp/Cntr=.3,.1

Type RM Length L Ch R = 1 ,7352.11 ,1013.97,1014.36,1015.16
XS GIS Cut Line= 4
     3196562.302    13798115.704     3196679.246    13796025.944
     3196681.026    13795980.832     3196741.209    13794358.649
#Sta/Elev= 30
 2886.05   24.72 2920.97   22.54 3028.39   23.52 3095.73   21.98 3477.26   23.87
 3772.81   22.41 3904.67   28.05 4435.71   27.95 4482.53   24.06 4932.09    24.8
 4977.43   26.28 4979.09   23.74 4999.71    21.1 5020.24   24.13 5022.57   26.44
 5029.44   27.32 5370.19   26.16 5431.76   28.07 5465.95   26.67 5578.65   27.98
 5615.16   26.95 6033.27    27.5 6069.02   28.97 6094.14    27.5 6149.82   27.35
  6208.6   27.49 6240.66   29.22 6260.96   27.67 6494.45   27.65 6647.52    16.5
#Mann= 3 ,-1 , 0
 2886.05     .07       0 4977.43    .032       0 5022.57     .07       0
#Block Obstruct= 3 ,-1
 2546.56 3923.08      28 4423.16 4974.08   26.68 6372.47 6763.83   28.23
Bank Sta=4977.43,5022.57
XS Rating Curve= 0
Exp/Cntr=.3,.1

Type RM Length L Ch R = 1 ,6337.751,1279.43,1330.85,1381.8
XS GIS Cut Line= 4
     3197605.928     13798175.34     3197690.425    13796083.934
      3197694.68    13796039.039     3197755.017    13794328.831
#Sta/Elev= 30
 2884.71   22.64 2918.29   20.88 2941.53   21.94 3190.28   23.81 3711.11   25.06
 3761.89   23.56 3837.51   23.53 4017.43   24.85  4144.5   24.07 4468.86   25.34
 4977.45   24.81 4980.79   22.16  4997.1   19.38 5020.11   21.75 5022.55   23.64
 5435.38   26.29 5868.39   25.83 5976.23   28.23 6021.06   27.51 6052.67   30.52
  6072.1   30.34 6107.13   27.56 6182.72   27.12 6254.93   29.36    6306   27.26
  6339.1    28.8  6355.2   27.52 6465.56    27.3 6524.23   28.67 6734.19   27.51
#Mann= 3 ,-1 , 0
 2884.71     .07       0 4977.45    .032       0 5022.55     .07       0
#Block Obstruct= 1 ,-1
 2040.49 4476.38   25.29
Bank Sta=4977.45,5022.55
XS Rating Curve= 0
Exp/Cntr=.3,.1

Type RM Length L Ch R = 1 ,5006.903,917.93,883.53,825.86
XS GIS Cut Line= 4
     3197755.017    13798160.431     3198941.124    13796322.798
     3199029.162    13796180.364     3199676.391    13795255.793
#Sta/Elev= 30
 2786.42   22.29 2807.64   20.97 2845.66    22.5 2916.04   22.49 3066.44   23.35
  3294.2   23.65 3551.39   23.49 3767.91   22.84 3852.11   22.19 4113.18    20.8
 4150.31   20.08 4382.24   19.46 4741.78    20.1  4900.8   19.97 4941.58   19.58
 4974.81   19.75 4978.24    19.2 4981.19   17.79 4989.73   16.59 5001.45   16.08
 5012.07    16.7 5017.19   17.65 5021.57   19.44 5025.19    20.1 5064.51   20.87
 5074.96      20 5141.39   20.01  5250.2   20.95 5719.53   22.56 6269.64   22.74
#Mann= 3 ,-1 , 0
 2786.42     .07       0 4974.81    .032       0 5025.19     .07       0
#XS Ineff= 1 ,-1
 4102.78 4743.45    20.1
Permanent Ineff=
       F
Bank Sta=4974.81,5025.19
XS Rating Curve= 0
Exp/Cntr=.3,.1

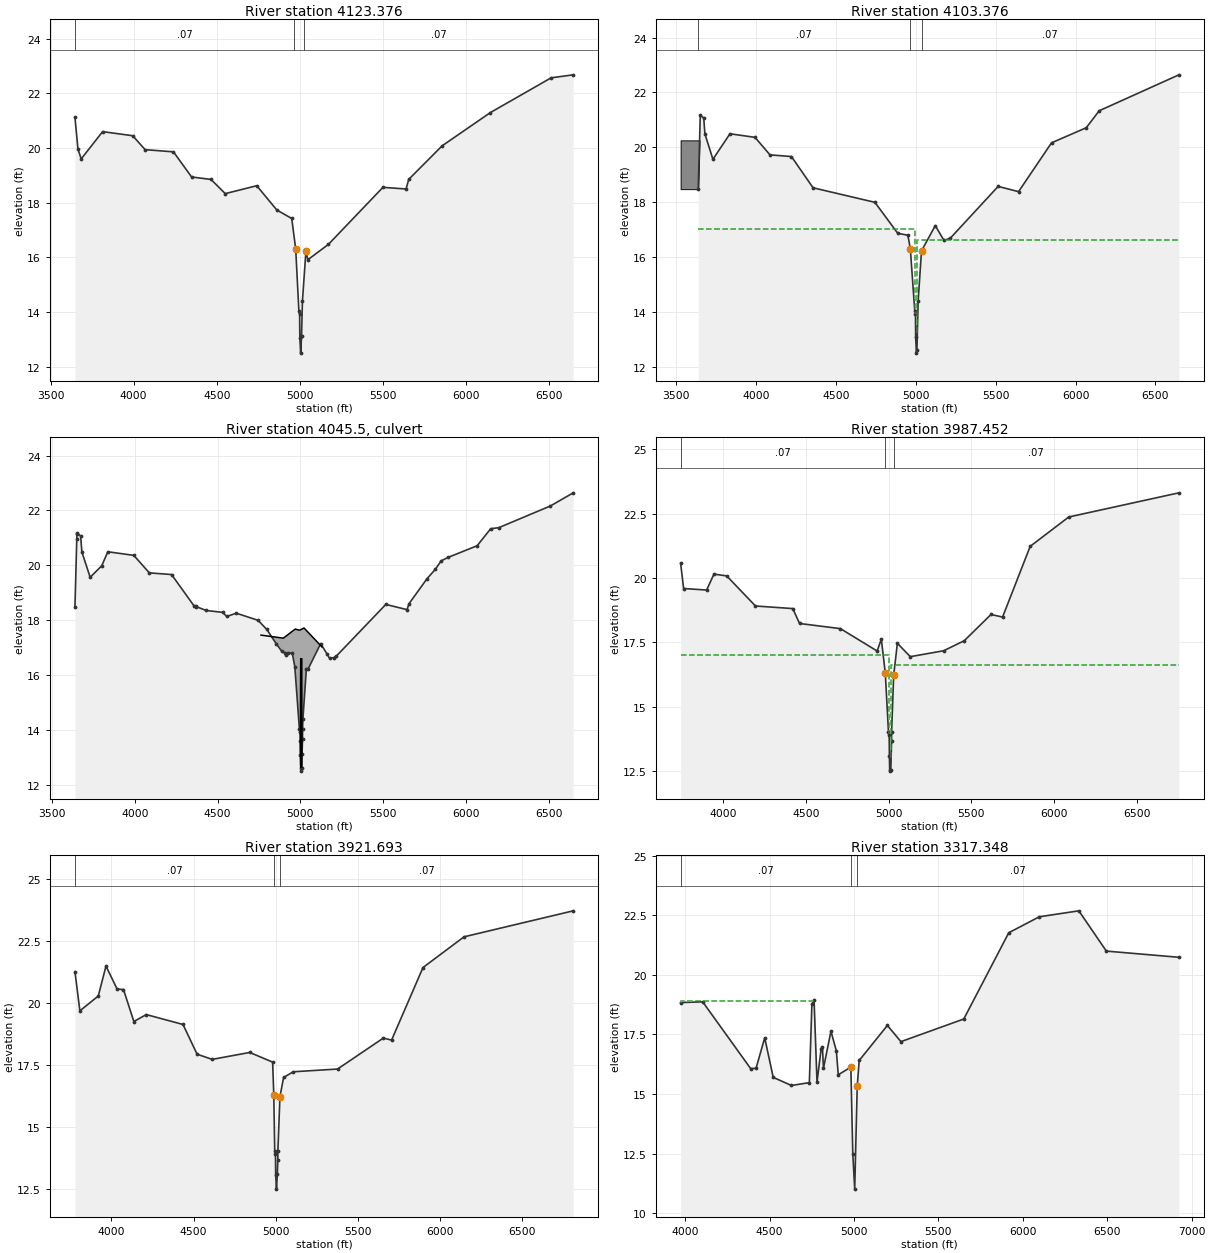
Type RM Length L Ch R = 1 ,4123.376,22.24,20,22.53
XS GIS Cut Line= 4
     3199532.169     13798258.28     3199570.066    13796933.142
     3199605.503    13796898.091     3199667.262    13795278.044
#Sta/Elev= 30
 3646.97   21.12 3665.11   19.96 3684.45    19.6 3813.21    20.6 3994.37   20.45
 4068.89   19.94 4239.44   19.86 4348.42   18.94 4465.03   18.85  4550.9   18.33
 4740.18   18.62 4861.07   17.73 4950.74   17.42 4974.64    16.3 4993.72   14.03
 4998.15   13.91 4999.45   13.06 5004.42   12.49 5009.69   13.12 5015.05    14.4
    5036   16.22 5047.66   15.91 5170.94   16.47 5499.14   18.56  5638.5    18.5
 5654.08   18.85 5855.05   20.08 6145.96    21.3 6510.65   22.57 6643.72   22.68
#Mann= 3 ,-1 , 0
 3646.97     .07       0 4965.54    .032       0 5025.47     .07       0
Bank Sta=4974.64,5036
XS Rating Curve= 0
Exp/Cntr=.5,.3

Type RM Length L Ch R = 1 ,4103.376,94.04,115.92,179.15
XS GIS Cut Line= 4
     3199549.935    13798281.968     3199585.693    13796945.816
     3199621.756    13796910.146     3199692.303    13795290.565
#Sta/Elev= 30
 3638.67   18.47 3651.37   21.16 3672.84   21.07  3680.5   20.48 3730.49   19.56
 3837.06   20.49 3993.74   20.36 4087.81   19.72 4221.93   19.66 4357.24   18.52
 4744.24   17.99 4887.39   16.86 4950.74   16.79    4966    16.3 4993.72   14.03
 4998.15   13.91 4999.45   13.06 5004.42   12.49  5007.3    12.6 5015.05    14.4
    5036   16.22 5122.19   17.14 5176.56    16.6 5215.96   16.68 5515.59   18.57
 5643.46   18.38 5849.86   20.16    6067   20.71 6148.42   21.33 6647.13   22.64
#Mann= 3 ,-1 , 0
 3638.67     .07       0    4966    .032       0    5036     .07       0
#XS Ineff= 2 , 0
       0    4998      17 5010.01       0   16.63
Permanent Ineff=
       F       F
#Block Obstruct= 1 ,-1
 3528.34 3660.59   20.25
Bank Sta=4966,5036
XS Rating Curve= 0
Exp/Cntr=.5,.3

Type RM Length L Ch R = 2 ,4045.5  ,,,
BEGIN DESCRIPTION:
Dirt Road
END DESCRIPTION:
Bridge Culvert--1,0,-1,-1, 0
Deck Dist Width WeirC Skew NumUp NumDn MinLoCord MaxHiCord MaxSubmerge Is_Ogee
38,15,2.6,0, 6, 6, , , .95, 0, 0,0,,
    4762    4897 4968.45 4994.94  5021.8    5130
   17.45   17.34   17.67   17.63   17.71   17.02
                                                
    4762    4897 4968.45 4994.94  5021.8    5130
   17.45   17.34   17.67   17.63   17.71   17.02
                                                
Multiple Barrel Culv=1,4,,15,.012,.2,1,1,3,12.61,12.61, 2,Culvert #1  , 0 ,38
    5002    5007    5007    5012
Culvert Bottom n=.012
BR U #Sta/Elev= 58
 3638.67   18.47 3649.56   20.94 3650.49   21.15 3651.37   21.16 3672.84   21.07
  3680.5   20.48 3730.49   19.56 3800.54   19.98 3837.06   20.49 3993.74   20.36
 4087.81   19.72 4221.93   19.66 4357.24   18.52 4369.21   18.52 4371.31   18.49
 4430.21   18.35 4530.56   18.28 4555.28   18.13 4612.78   18.25 4744.24   17.99
 4796.48   17.66 4855.48   17.12 4887.39   16.86 4904.18    16.8 4914.97   16.72
 4925.66   16.79 4950.74   16.79    4966    16.3 4993.72   14.03 4998.15   13.91
 4998.45   13.59 4999.45   13.06  5001.7   12.61 5004.42   12.49  5007.3    12.6
 5009.69   13.12 5012.58   13.65 5012.84   14.02 5015.05    14.4    5036   16.22
 5047.66   16.23 5122.19   17.14    5160   16.77 5176.56    16.6 5200.73   16.63
 5215.96   16.68 5515.59   18.57 5643.46   18.38 5655.96    18.6 5764.59   19.51
 5814.34   19.85 5849.86   20.16 5893.53   20.29    6067   20.71 6148.42   21.33
 6198.08   21.37 6508.97   22.16 6647.13   22.64
BR U #Mann= 3
 3638.67     .07    4966    .032    5036     .07
BR D #Sta/Elev= 49
  3741.2   20.57 3749.01   20.12 3759.34   19.59 3826.59   19.55 3882.48   19.59
 3898.47   19.53 3942.93   20.15 4019.96   20.08 4178.88   18.97 4186.59   18.97
 4194.04   18.91 4419.72   18.81 4460.93   18.23 4599.84    17.9 4607.71   17.91
  4621.7   17.93  4708.2   18.03 4855.87    17.4 4879.23   17.45 4892.78   17.44
 4930.14   17.16 4930.66   17.29 4955.74   17.62 4979.64    16.3 4998.72   14.03
 5003.15   13.91 5003.45   13.59 5004.45   13.06 5009.42   12.49 5014.69   13.12
 5017.58   13.65 5017.84   14.02 5020.05    14.4 5030.36   16.22 5052.66   17.46
 5112.49   17.13  5130.9   16.94 5332.68   17.17 5457.39   17.56 5619.28   18.58
 5689.27   18.48 5796.42   20.42 5856.46   21.23 6089.63   22.37 6146.53   22.53
 6165.55   22.58 6174.62   22.64 6627.52   22.99 6756.28   23.31
BR D #Mann= 3
  3741.2     .07 4979.64    .032 5030.36     .07
BC Design=,, 0 ,, 0 ,,,,,,
BC HTab HWMax=22.64

Type RM Length L Ch R = 1 ,3987.452,74.44,65.76,49.64
XS GIS Cut Line= 4
     3199606.196     13798258.28     3199650.613    13797059.037
      3199754.03    13796922.576     3199811.332    13795279.779
#Sta/Elev= 30
  3741.2   20.57 3759.34   19.59 3898.47   19.53 3942.93   20.15 4019.96   20.08
 4194.04   18.91 4419.72   18.81 4460.93   18.23  4708.2   18.03 4930.14   17.16
 4955.74   17.62 4979.64    16.3 4998.72   14.03 5003.15   13.91 5004.45   13.06
 5006.16   12.55 5009.42   12.49 5012.96   12.54 5017.58   13.65 5017.84   14.02
 5030.36   16.22 5052.66   17.46  5130.9   16.94 5332.68   17.17 5457.39   17.56
 5619.28   18.58 5689.27   18.48 5856.46   21.23 6089.63   22.37 6756.28   23.31
#Mann= 3 ,-1 , 0
  3741.2     .07       0 4979.64    .032       0 5030.36     .07       0
#XS Ineff= 2 , 0
       0    5002      17 5014.91       0   16.63
Permanent Ineff=
       F       F
Bank Sta=4979.64,5030.36
XS Rating Curve= 0
Exp/Cntr=.5,.3

Type RM Length L Ch R = 1 ,3921.693,633.98,604.34,584.43
XS GIS Cut Line= 4
     3199692.068    13798270.124     3199709.437    13797109.309
     3199789.677    13796953.742     3199868.039    13795260.353
#Sta/Elev= 30
 3778.43   21.27 3808.41   19.69 3920.38   20.29 3967.16    21.5 4034.93   20.57
 4073.71   20.55 4136.81   19.26 4212.36   19.54 4435.82   19.14 4521.32   17.94
 4613.17   17.73 4841.57   18.01    4981   17.62    4988    16.3 4993.72   14.03
 4998.15   13.91 4999.45   13.06 5004.42   12.49 5009.69   13.12 5012.58   13.65
 5012.84   14.02 5025.36   16.22 5047.66      17 5106.61   17.23 5375.94   17.34
 5654.29   18.59 5704.62   18.51 5895.67   21.44 6145.27   22.68 6809.62   23.73
#Mann= 3 ,-1 , 0
 3778.43     .07       0    4988    .032       0 5025.36     .07       0
Bank Sta=4988,5025.36
XS Rating Curve= 0
Exp/Cntr=.3,.1

Type RM Length L Ch R = 1 ,3317.348,18.77,20.37,26.26
XS GIS Cut Line= 4
     3200177.171    13798261.459     3200304.277    13797273.287
     3200299.438    13797212.623     3200994.998    13795450.178
#Sta/Elev= 30
 3972.74   18.84 4103.55   18.87 4387.44   16.07  4419.5   16.08 4470.84   17.36
 4521.28    15.7 4629.41   15.36 4735.28   15.48  4750.4   18.77 4763.22   18.95
 4780.65    15.5 4805.31   16.91 4812.73   16.97 4818.97   16.08 4863.23   17.64
 4895.29   16.81 4906.53   15.81 4981.18   16.13 4992.65   12.49 5004.02   11.01
 5018.82   15.32 5030.66   16.41  5197.6   17.88 5277.81    17.2 5650.27   18.15
 5916.65   21.77 6097.31   22.44 6331.79   22.69 6494.73      21 6924.64   20.74
#Mann= 3 ,-1 , 0
 3972.74     .07       0 4981.18    .032       0 5018.82     .07       0
#XS Ineff= 1 ,-1
 3859.02 4760.99    18.9
Permanent Ineff=
       F
#Block Obstruct= 2 , 0
          4757.5   18.37
Bank Sta=4981.18,5018.82
XS Rating Curve= 0
Exp/Cntr=.5,.3

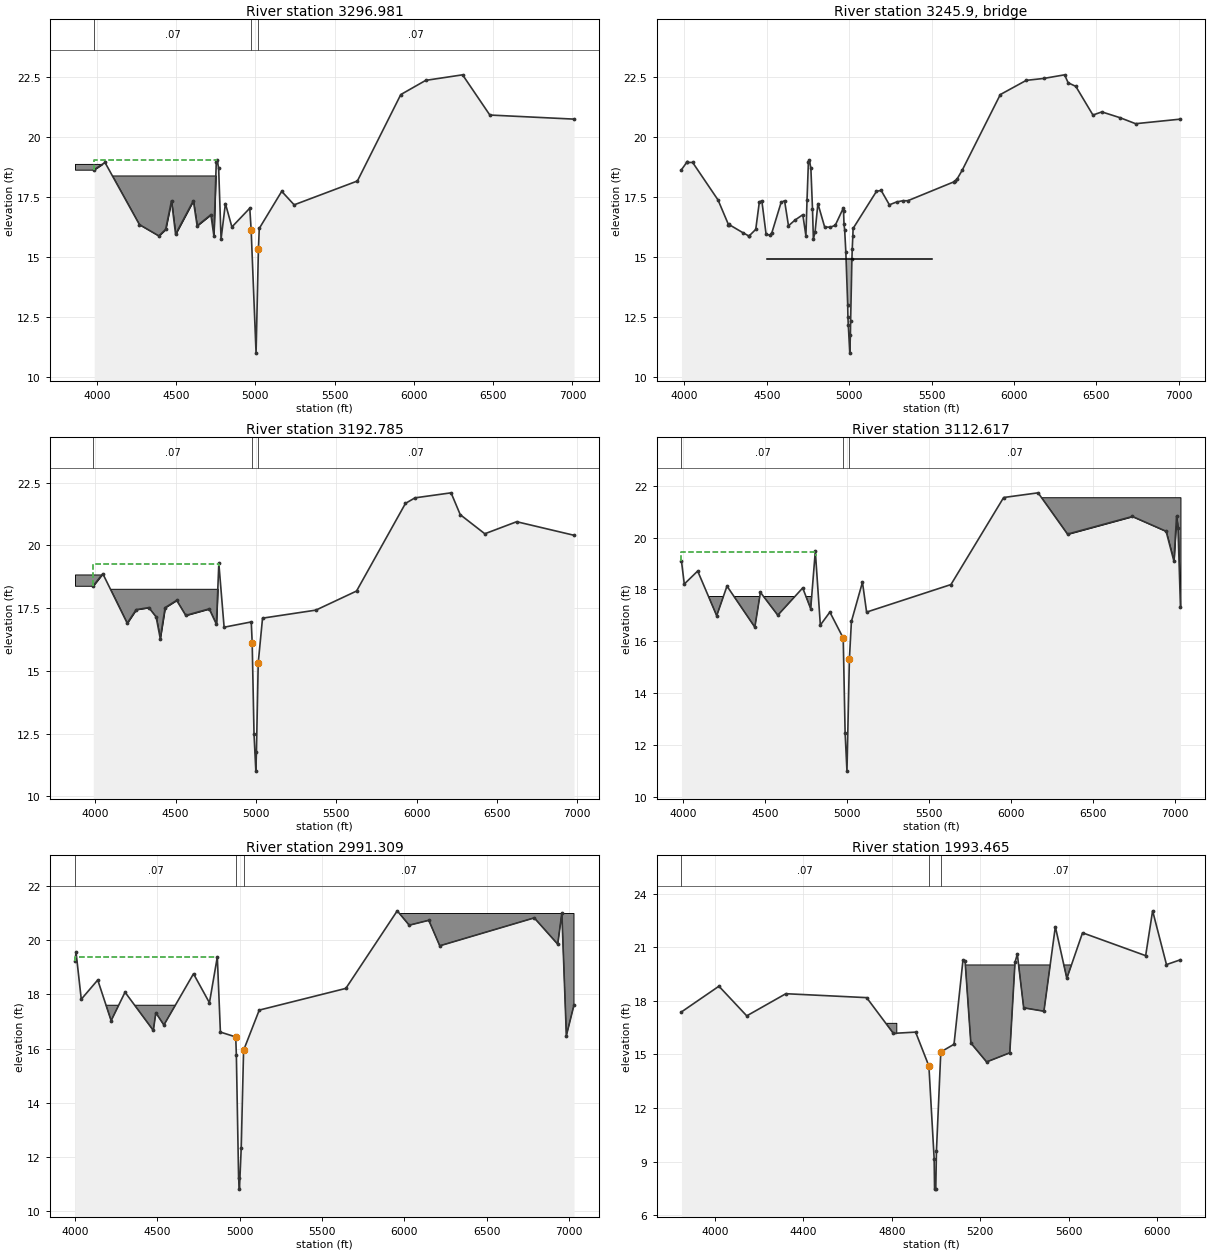
Type RM Length L Ch R = 1 ,3296.981,72.06,104.2,111.11
XS GIS Cut Line= 4
     3200209.117    13798255.069     3200323.437    13797263.528
     3200320.618    13797225.993     3201052.416    13795374.358
#Sta/Elev= 30
 3983.01   18.63 4050.88   18.93    4268   16.35 4390.61   15.88 4433.61   16.15
 4470.54   17.34  4496.3   15.95 4608.44   17.34  4632.2    16.3 4719.13   16.76
 4737.89   15.88 4752.99   18.94 4759.08   19.02 4768.09   18.68 4783.19   15.75
 4810.62   17.22 4851.56   16.25 4964.39   17.03    4973   16.13 5004.02   11.01
 5018.82   15.32 5024.17   16.19 5165.88   17.73 5244.25   17.17 5643.31   18.16
 5916.96   21.75 6074.42   22.34 6306.84   22.57 6478.81    20.9 7009.76   20.73
#Mann= 3 ,-1 , 0
 3983.01     .07       0    4973    .032       0 5018.82     .07       0
#XS Ineff= 1 ,-1
 3969.88 4758.43   19.03
Permanent Ineff=
       F
#Block Obstruct= 2 ,-1
 3861.67 4034.41   18.87 3983.01 4752.36   18.39
Bank Sta=4973,5018.82
XS Rating Curve= 0
Exp/Cntr=.5,.3

Type RM Length L Ch R = 3 ,3245.9  ,,,
BEGIN DESCRIPTION:
Pipe combination, Footbridge at location deemed insignificant and not modeled
END DESCRIPTION:
Bridge Culvert--1,0,-1,-1, 0
Deck Dist Width WeirC Skew NumUp NumDn MinLoCord MaxHiCord MaxSubmerge Is_Ogee
39,2,2.6,0, 2, 2, , , .95, 0, 0,0,,
    4500    5500
    14.9    14.9
    12.9    12.9
    4500    5500
    14.9    14.9
    12.9    12.9
BR Coef=-1 , 0 , 0 ,, 0 ,,,.8,-1,,0,
WSPro=,,,, 1 ,,,, 0 ,,,, 0 ,,,,-1 ,-1 ,-1 , 0 , 0 , 0 , 0 , 0
BR U #Sta/Elev= 70
 3983.01   18.63 4014.73   18.93  4019.6   18.93 4050.88   18.93 4205.02   17.37
    4268   16.35 4269.25   16.36 4271.93   16.35 4353.78   16.02 4390.61   15.88
 4393.71   15.88 4433.61   16.15 4455.43   17.29 4470.54   17.34  4496.3   15.95
 4519.27   15.91 4531.81   16.02 4587.51   17.27 4608.44   17.34  4632.2    16.3
 4672.36   16.54 4719.13   16.76 4737.89   15.88 4744.54   17.35 4752.99   18.94
 4759.08   19.02 4768.09   18.68 4777.82      17 4783.19   15.75 4793.52   16.05
 4810.62   17.22 4851.56   16.25  4885.7   16.24 4915.92   16.32 4964.39   17.03
 4966.26   16.91    4969   16.36    4973   16.13    4980   15.21 4991.46   12.99
 4992.65   12.49 4995.13   12.17 5004.02   11.01 5007.66   11.76 5009.07   12.34
 5016.99   14.92 5018.82   15.32 5022.53   15.89 5024.17   16.19 5165.88   17.73
 5194.11   17.77 5244.25   17.17 5288.25   17.29 5326.23   17.34 5355.84   17.34
 5633.89   18.12 5643.31   18.16 5656.28   18.26 5686.13   18.61 5916.96   21.75
 6074.42   22.34 6180.35   22.42 6306.84   22.57 6328.58   22.24    6375   22.09
 6478.81    20.9 6533.06   21.03 6642.76   20.79 6737.78   20.54 7009.76   20.73
BR U #Mann= 3
 3983.01     .07    4973    .032 5018.82     .07
BR D #Sta/Elev= 70
    3987   18.39 4013.15   18.65 4026.86   18.65 4035.31   18.75 4046.34   18.87
 4165.15   17.29  4193.2   16.99 4198.06    16.9 4254.25   17.44 4332.69   17.52
  4378.2   17.15  4403.8   16.29 4426.26   17.18  4434.2   17.52 4505.97   17.81
 4515.72   17.74 4562.56   17.21 4613.41   17.41 4664.09   17.48 4708.69   17.47
 4739.49   16.83 4753.41   16.86 4760.34   17.95 4768.61   19.28 4786.81   17.75
 4795.41   17.25 4801.46   16.74 4811.94   16.74 4861.22    16.9 4930.93   16.95
 4970.46   16.95 4971.57   16.73    4974   16.36 4976.18   16.13 4979.74   15.21
 4986.46   12.99 4987.65   12.49 4990.13   12.17 4999.02   11.01 5002.66   11.76
 5004.07   12.34 5011.99   14.92 5013.82   15.32 5028.43   16.41 5034.07   16.65
 5034.42   16.71 5036.31   17.05 5040.67    17.1 5073.68   17.13 5096.17   17.16
 5109.05   17.01 5213.31   17.29 5302.96   17.42 5372.64   17.42  5577.5      18
 5625.94   18.18 5692.45   18.74 5844.57    20.5 5930.56   21.67  5989.7   21.89
 6152.23   22.01  6214.4   22.09 6271.56   21.22 6393.17   20.82 6424.45   20.46
 6622.78   20.94 6686.53    20.8 6863.04   20.34 6964.51   20.41 6979.63    20.4
BR D #Mann= 3
    3987     .07 4976.18    .032 5013.82     .07
BC Design=,, 0 ,, 0 ,,,,,,
BC HTab HWMax=22.57

Type RM Length L Ch R = 1 ,3192.785,80.78,80.17,80.69
XS GIS Cut Line= 4
     3200234.674    13798261.459     3200387.439    13797329.969
     3200448.391    13797200.894     3201142.462    13795425.813
#Sta/Elev= 30
    3987   18.39 4046.34   18.87 4198.06    16.9 4254.25   17.44 4332.69   17.52
  4378.2   17.15  4403.8   16.29  4434.2   17.52 4505.97   17.81 4562.56   17.21
 4708.69   17.47 4753.41   16.86 4768.61   19.28 4801.46   16.74 4970.46   16.95
 4976.18   16.13 4987.65   12.49 4999.02   11.01 5002.66   11.76 5013.82   15.32
 5040.67    17.1 5372.64   17.42 5625.94   18.18 5930.56   21.67  5989.7   21.89
  6214.4   22.09 6271.56   21.22 6424.45   20.46 6622.78   20.94 6979.63    20.4
#Mann= 3 ,-1 , 0
    3987     .07       0 4976.18    .032       0 5013.82     .07       0
#XS Ineff= 1 ,-1
 3948.94 4767.86   19.27
Permanent Ineff=
       F
#Block Obstruct= 2 ,-1
 3873.14 4047.91   18.84    3987  4775.3   18.27
Bank Sta=4976.18,5013.82
XS Rating Curve= 0
Exp/Cntr=.5,.3

Type RM Length L Ch R = 1 ,3112.617,124.93,121.31,113.69
XS GIS Cut Line= 4
     3200253.842    13798287.016     3200461.402    13797360.693
     3200521.929    13797232.519     3201232.509     13795412.95
#Sta/Elev= 30
 3989.25    19.1 4006.53   18.21 4088.24   18.71 4204.34   16.99    4267   18.13
 4436.95   16.55 4471.05   17.89 4577.06   17.01 4729.01   18.06 4777.73   17.26
 4805.87   19.47 4836.62   16.63 4894.78   17.13 4976.18   16.13 4987.65   12.49
 4999.02   11.01 5013.82   15.32 5026.15   16.77 5093.57   18.28 5118.76   17.13
 5633.47   18.19 5954.97   21.54 6165.11   21.72 6344.61   20.13 6740.66   20.81
 6946.02   20.24 6993.75   19.09 7009.85   20.82 7018.67   20.36 7033.68   17.34
#Mann= 3 ,-1 , 0
 3989.25     .07       0 4976.18    .032       0 5013.82     .07       0
#XS Ineff= 1 ,-1
 3944.31 4807.74   19.46
Permanent Ineff=
       F
#Block Obstruct= 2 ,-1
 3883.27 4800.94   17.73  6074.9 7033.68   21.55
Bank Sta=4976.18,5013.82
XS Rating Curve= 0
Exp/Cntr=.3,.1

Type RM Length L Ch R = 1 ,2991.309,1092.17,997.84,894.66
XS GIS Cut Line= 4
     3200266.621    13798306.184      3200588.68    13797383.701
     3200604.732    13797338.736     3201283.963    13795451.541
#Sta/Elev= 30
 3999.93   19.24 4006.32   19.55 4038.09   17.82 4138.08   18.53 4219.47   17.03
 4303.84   18.08 4475.63   16.67 4490.96   17.32 4539.88   16.87 4719.65   18.76
 4816.48   17.69 4864.26   19.38    4883   16.61 4976.13   16.43 4979.91   15.77
 4993.52   11.24 4998.67   10.82 5009.47   12.33 5023.87   15.94 5118.91   17.42
 5644.76   18.22    5957   21.08 6029.71   20.55 6148.63   20.73 6215.23   19.79
 6789.14   20.82 6931.67   19.85 6956.79      21 6984.12   16.48 7030.47   17.61
#Mann= 3 ,-1 , 0
 3999.93     .07       0 4976.13    .032       0 5023.87     .07       0
#XS Ineff= 1 ,-1
 3973.73 4863.97   19.37
Permanent Ineff=
       F
#Block Obstruct= 2 ,-1
  3796.9 4844.13    17.6 5956.14 7030.47   20.98
Bank Sta=4976.13,5023.87
XS Rating Curve= 0
Exp/Cntr=.3,.1

Type RM Length L Ch R = 1 ,1993.465,308.68,314.64,287.77
XS GIS Cut Line= 4
     3202123.918    13798311.179     3201604.611    13797313.233
     3201562.858    13797279.118     3200988.097    13796364.866
#Sta/Elev= 30
 3848.01   17.38 4017.65   18.82 4143.56   17.16 4320.54    18.4 4686.27   18.18
 4807.17   16.18 4907.96   16.25 4968.04   14.35 4991.83    9.17 4993.75    7.46
 4999.24    7.47 5002.19    9.58 5021.96   15.14 5081.78   15.57 5122.33   20.28
 5131.99   20.21 5157.94   15.64  5229.3   14.58 5334.26   15.09  5357.8   20.15
  5368.3   20.62 5397.14   17.61 5488.79   17.42 5540.47   22.15 5592.45   19.26
 5663.53   21.81 5949.29   20.53 5980.75   23.04 6043.51   20.03 6106.82    20.3
#Mann= 3 ,-1 , 0
 3848.01     .07       0 4968.04    .032       0 5021.96     .07       0
#Block Obstruct= 2 ,-1
  4774.3 4820.59   16.77 5127.53 6106.82   20.01
Bank Sta=4968.04,5021.96
XS Rating Curve= 0
Exp/Cntr=.3,.1

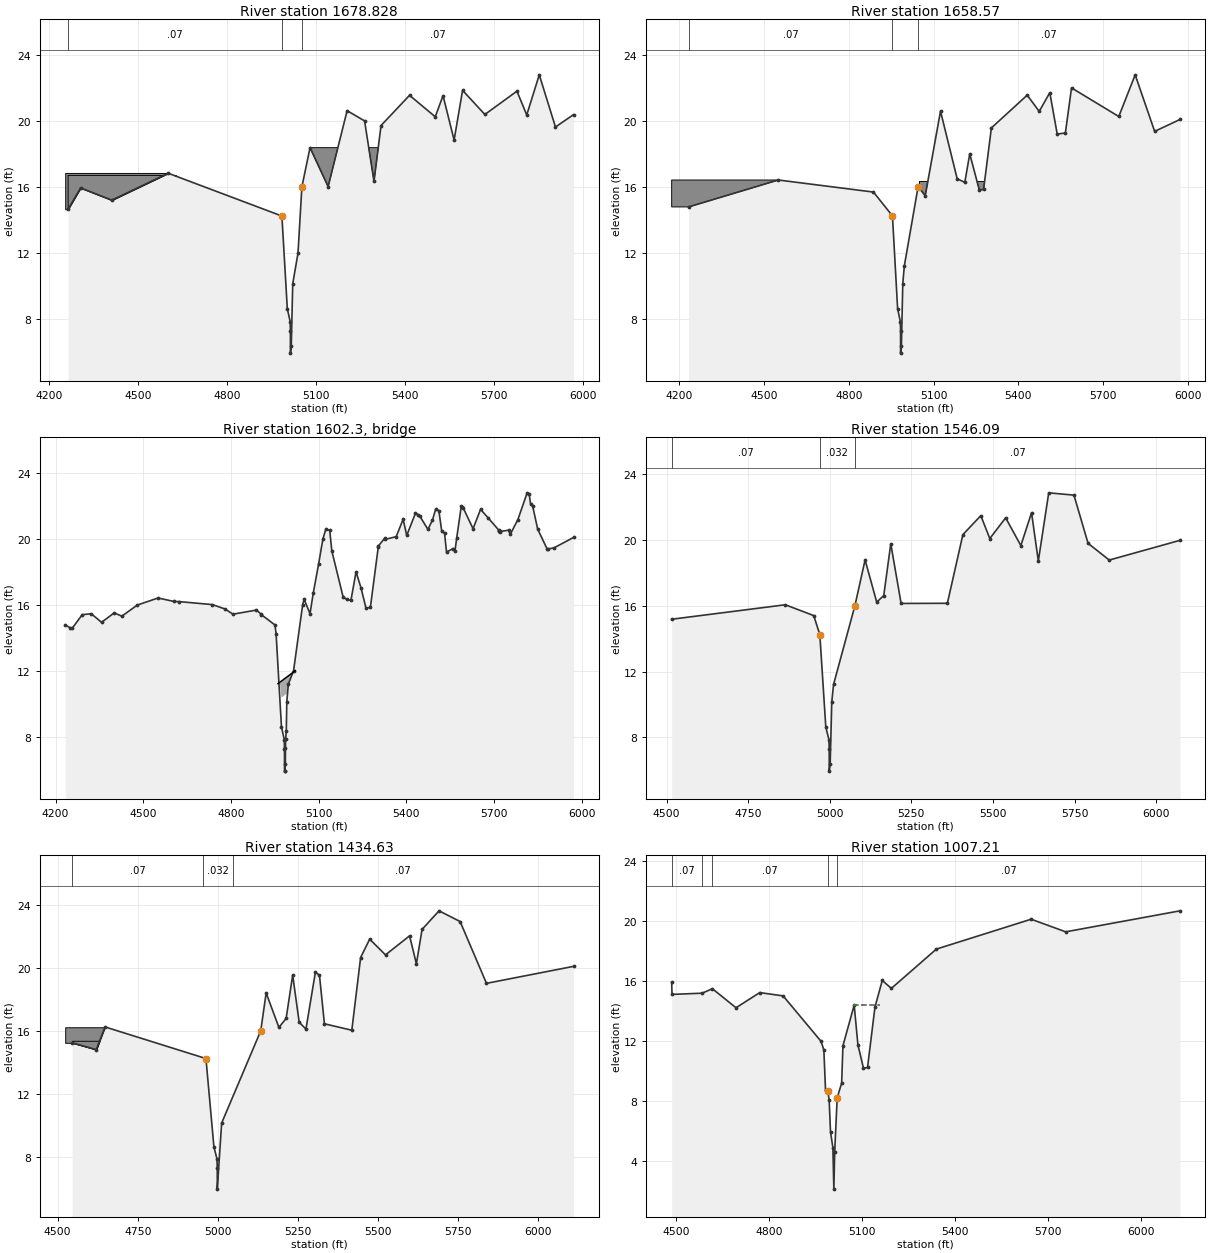
Type RM Length L Ch R = 1 ,1678.828,25.88,20.26,20.82
XS GIS Cut Line= 4
     3202159.644    13797575.105     3201698.002    13797020.905
     3201634.974    13796955.448     3201000.669    13796325.487
#Sta/Elev= 30
 4262.95   14.66 4305.13   15.95 4410.61   15.21    4601   16.84  4984.6   14.25
 5002.85    8.64 5012.49    7.86 5013.28    7.28  5013.4    5.95 5016.21    6.36
 5021.17   10.15    5039   12.01    5052   16.01 5079.54   18.39 5140.66   16.03
 5204.74   20.63  5263.7   20.01 5295.48   16.35 5319.25   19.73 5415.51   21.56
 5502.28   20.26 5528.52   21.54 5565.92   18.85 5594.55   21.86 5669.78    20.4
 5778.05   21.81 5811.08   20.37 5853.41    22.8 5908.09   19.64 5969.08   20.39
#Mann= 3 ,-1 , 0
 4262.95     .07       0  4984.6    .032       0    5052     .07       0
#Block Obstruct= 3 ,-1
 4253.08 4600.86   16.86 4262.95 4627.53   16.71 5079.02 5397.88   18.39
Bank Sta=4984.6,5052
XS Rating Curve= 0
Exp/Cntr=.5,.3

Type RM Length L Ch R = 1 ,1658.57 ,140.16,112.48,114.86
XS GIS Cut Line= 4
     3202175.011    13797562.304     3201712.908    13797007.552
     3201649.926    13796942.142     3201011.753    13796270.066
#Sta/Elev= 30
 4232.84   14.79 4550.53   16.42  4887.3   15.69  4954.6   14.25 4972.85    8.64
 4982.49    7.86 4983.28    7.28  4983.4    5.95 4986.21    6.36 4991.17   10.15
 4996.58   11.22  5045.4   16.01 5070.67   15.47 5124.69   20.58 5183.77   16.49
 5210.69   16.28 5228.19      18 5262.14   15.81 5277.16   15.85 5304.81   19.57
 5431.56   21.55 5474.13   20.57 5511.57    21.7 5537.79    19.2 5566.67   19.26
 5588.46   21.99 5755.76   20.26 5813.78   22.78 5882.69   19.36 5972.44   20.08
#Mann= 3 ,-1 , 0
 4232.84     .07       0  4954.6    .032       0  5045.4     .07       0
#Block Obstruct= 2 ,-1
 4173.06 4550.75   16.42  5050.2 5438.87   16.33
Bank Sta=4954.6,5045.4
XS Rating Curve= 0
Exp/Cntr=.5,.3

Type RM Length L Ch R = 3 ,1602.3  ,,,
BEGIN DESCRIPTION:
metal grated foot bridge
END DESCRIPTION:
Bridge Culvert--1,0,-1,-1, 0
Deck Dist Width WeirC Skew NumUp NumDn MinLoCord MaxHiCord MaxSubmerge Is_Ogee
65,2,2.6,0, 2, 2, , , .95, 0, 0,0,,
    4961    5020
   11.24   12.02
   10.24   11.02
    4978    5028
   11.24   12.02
   10.24   11.02
BR Coef=-1 , 0 , 0 ,, 0 ,,,.8,-1,,0,
WSPro=,,,, 1 ,,,, 0 ,,,, 0 ,,,,-1 ,-1 ,-1 , 0 , 0 , 0 , 0 , 0
BR U #Sta/Elev= 91
 4232.84   14.79 4249.92   14.62 4256.33   14.58 4291.15   15.41 4321.86   15.47
 4357.29   14.95 4400.62   15.52 4426.66   15.32  4479.3   15.99 4550.53   16.42
 4605.36   16.21 4623.88    16.2 4736.63   16.02 4780.53   15.75 4806.65   15.44
  4887.3   15.69 4904.02   15.43 4904.15   15.41  4950.6   14.79  4954.6   14.25
 4972.85    8.64 4982.49    7.86 4983.28    7.28  4983.4    5.95 4984.62    5.97
 4986.21    6.36 4986.62    7.33 4987.15    7.87 4989.47    8.39 4991.17   10.15
 4996.58   11.22 5014.23   12.01  5045.4   16.01 5050.45   16.34 5070.67   15.47
 5081.55    16.7 5100.17   18.49 5114.72   19.99 5124.69   20.58 5138.03   20.52
 5145.21   19.27 5183.77   16.49 5195.85   16.33 5210.69   16.28 5228.19      18
 5245.34   17.02 5262.14   15.81 5277.16   15.85 5304.36   19.52 5304.81   19.57
 5325.58   20.02 5327.05   19.96 5365.56   20.13 5389.25   21.18 5401.55    20.2
 5431.56   21.55 5441.06   21.46 5445.94   21.38 5474.13   20.57 5489.67   21.13
 5500.44   21.78 5511.57    21.7 5521.47   20.45 5531.04   20.34 5537.79    19.2
 5560.29   19.41 5566.67   19.26 5572.41   20.02 5588.46   21.99 5590.84   21.92
 5594.54   21.88 5628.64   20.61 5654.27   21.78 5680.44   21.26  5716.3   20.53
 5717.21   20.46 5718.65   20.48 5719.16   20.46 5721.33   20.44 5749.99   20.52
 5755.76   20.26 5781.93   21.16 5813.78   22.78 5820.63   22.69  5825.3   22.12
 5832.79   21.96 5849.67   20.59 5882.69   19.36 5886.35   19.39 5905.38   19.45
 5972.44   20.08
BR U #Mann= 3
 4232.84     .07  4954.6    .032  5045.4     .07
BR D #Sta/Elev= 81
 4515.72   15.19 4562.45   14.78 4614.15   14.86 4630.61   15.54 4658.54   15.09
 4686.43   14.95 4777.39   15.91 4835.86   15.99 4863.92   16.07 4887.95   15.38
 4930.79   15.18 4932.92   15.27  4944.2   15.47    4951   15.41  4965.6   14.79
  4969.6   14.25 4987.85    8.64 4997.49    7.86 4998.28    7.28  4998.4    5.95
 4999.62    5.97 5001.21    6.36 5001.62    7.33 5002.15    7.87 5004.47    8.39
 5006.17   10.15 5011.58   11.22 5029.23   12.01    5077   16.01 5108.24    18.8
 5109.39   18.73 5143.82   16.23 5157.08    16.6 5165.37   16.63 5178.01   18.41
 5186.91   19.78 5198.94   17.76 5218.55   16.15 5250.99   16.05 5256.71   16.58
 5262.95   16.04 5291.69   16.03 5326.82    16.1 5352.74   16.17 5360.26   16.16
 5373.94   16.54 5394.73   19.62 5401.26   19.25 5407.85   20.34 5427.68    20.2
 5458.43   21.16 5462.74   21.49 5471.03   20.98 5474.83   21.26 5490.28    20.1
 5495.18   20.22 5529.33    21.3 5538.82   21.36 5556.22   20.53 5585.34   19.67
 5595.93   20.67 5607.06   21.74 5618.13   21.67 5637.61   18.92 5638.91   18.73
 5640.32   18.85 5643.57   19.28 5662.52   21.55 5670.76   22.88 5678.31   22.62
 5696.82    22.2 5748.02   22.74 5768.64   22.05 5791.25   19.81 5824.09   19.27
 5856.05   18.79 5867.71   19.02 5887.63   19.15 5953.59   19.38 6068.07   19.99
 6072.89   19.99
BR D #Mann= 3
 4515.72     .07  4969.6    .032    5077     .07
BC Design=,, 0 ,, 0 ,,,,,,
BC HTab HWMax=22.78

Type RM Length L Ch R = 1 ,1546.09 ,102.55,111.46,106.61
XS GIS Cut Line= 3
     3202219.928    13797120.776     3201829.165    13796974.621
     3201058.861    13796134.285
#Sta/Elev= 30
 4515.72   15.19 4863.92   16.07    4951   15.41  4969.6   14.25 4987.85    8.64
 4997.49    7.86 4998.28    7.28  4998.4    5.95 5001.21    6.36 5006.17   10.15
 5011.58   11.22    5077   16.01 5108.24    18.8 5143.82   16.23 5165.37   16.63
 5186.91   19.78 5218.55   16.15 5360.26   16.16 5407.85   20.34 5462.74   21.49
 5490.28    20.1 5538.82   21.36 5585.34   19.67 5618.13   21.67 5638.91   18.73
 5670.76   22.88 5748.02   22.74 5791.25   19.81 5856.05   18.79 6072.89   19.99
#Mann= 3 ,-1 , 0
 4515.72     .07       0  4969.6    .032       0    5077     .07       0
#Block Obstruct= 2 , 0
         4844.53   16.04 5184.62           19.17
Bank Sta=4969.6,5077
XS Rating Curve= 0
Exp/Cntr=.5,.3

Type RM Length L Ch R = 1 ,1434.63 ,349.25,427.42,491.71
XS GIS Cut Line= 3
      3202225.47    13797118.005     3201898.674    13796883.031
     3201072.716    13796065.009
#Sta/Elev= 30
 4545.37   15.25 4620.61   14.82 4647.94   16.26    4963   14.25 4987.85    8.64
 4997.49    7.86 4998.28    7.28  4998.4    5.95    5012   10.15    5134   16.01
 5150.92   18.42 5190.68   16.23 5213.32    16.8 5233.72   19.55 5254.01   16.56
 5275.12   16.12 5304.59   19.74 5317.35   19.54 5332.82   16.46 5418.31   16.05
 5445.78   20.67 5474.02   21.84 5523.44   20.84 5598.56   22.05 5619.88   20.27
 5637.59   22.46 5690.62   23.64 5756.34   22.96 5838.62   19.03 6110.36   20.11
#Mann= 3 ,-1 , 0
 4545.37     .07       0 4952.27    .032       0 5046.17     .07       0
#Block Obstruct= 2 ,-1
 4523.69 4648.09   16.24 4545.37 4723.08   15.38
Bank Sta=4963,5134
XS Rating Curve= 0
Exp/Cntr=.3,.1

Type RM Length L Ch R = 1 ,1007.21 ,31.23,40.41,43.9
XS GIS Cut Line= 4
     3202170.049    13797068.126     3202131.509      13796593.6
     3202111.098    13796537.904     3202146.624    13795435.687
#Sta/Elev= 30
 4486.43   15.95 4487.51   15.13 4584.72   15.21 4617.49   15.51 4693.82   14.24
 4770.34   15.25 4845.58   15.03 4967.89      12 4976.84   11.43  4982.3    8.73
 4990.12    8.66 4993.95    8.08 4998.34    5.96 5005.92    4.92 5009.11    2.15
 5011.82    4.64 5019.88    8.24 5034.21    9.22 5038.42   11.71 5074.62   14.41
 5086.65   11.77 5104.63    10.2 5117.67   10.26 5141.55   14.28 5165.11   16.06
 5194.43   15.53 5339.58   18.15 5644.92   20.14 5756.36    19.3 6124.63    20.7
#Mann= 5 ,-1 , 0
 4486.43     .07       0 4584.72     .12       0 4617.49     .07       0
 4990.12    .032       0 5019.88     .07       0
#XS Ineff= 1 ,-1
 5074.24 5159.21   14.39
Permanent Ineff=
       F
Bank Sta=4990.12,5019.88
XS Rating Curve= 0
Exp/Cntr=.5,.3