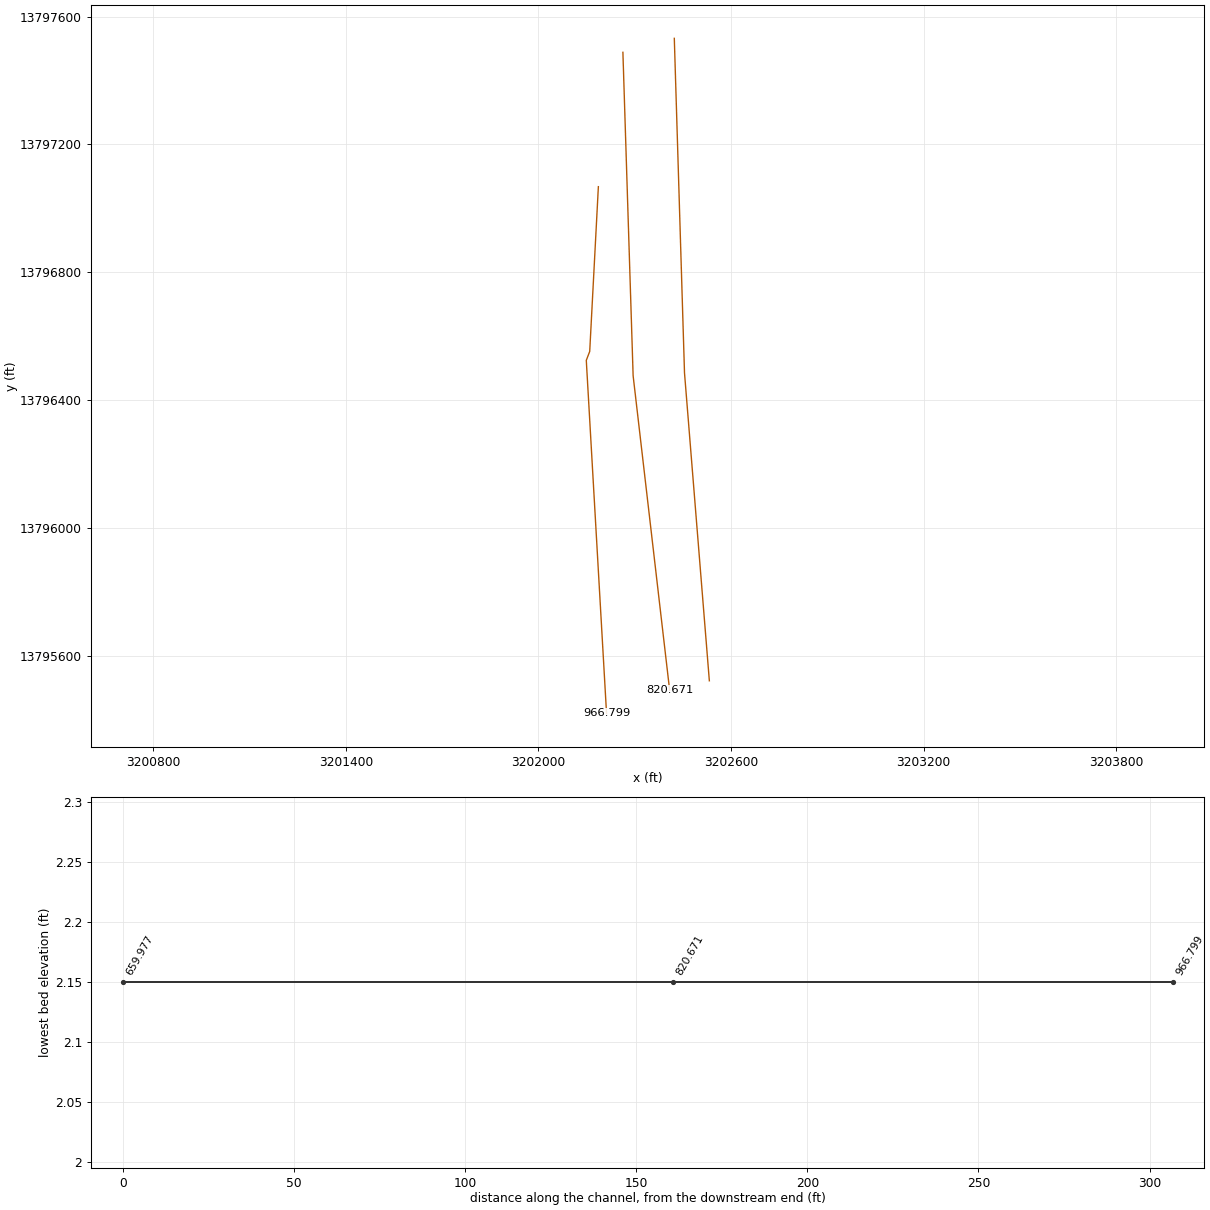
HEC-RAS study B111-00-00_Updated.prj: B111-00-00

--- B111-00-00_Updated.g04 (geometry) --- (continued)

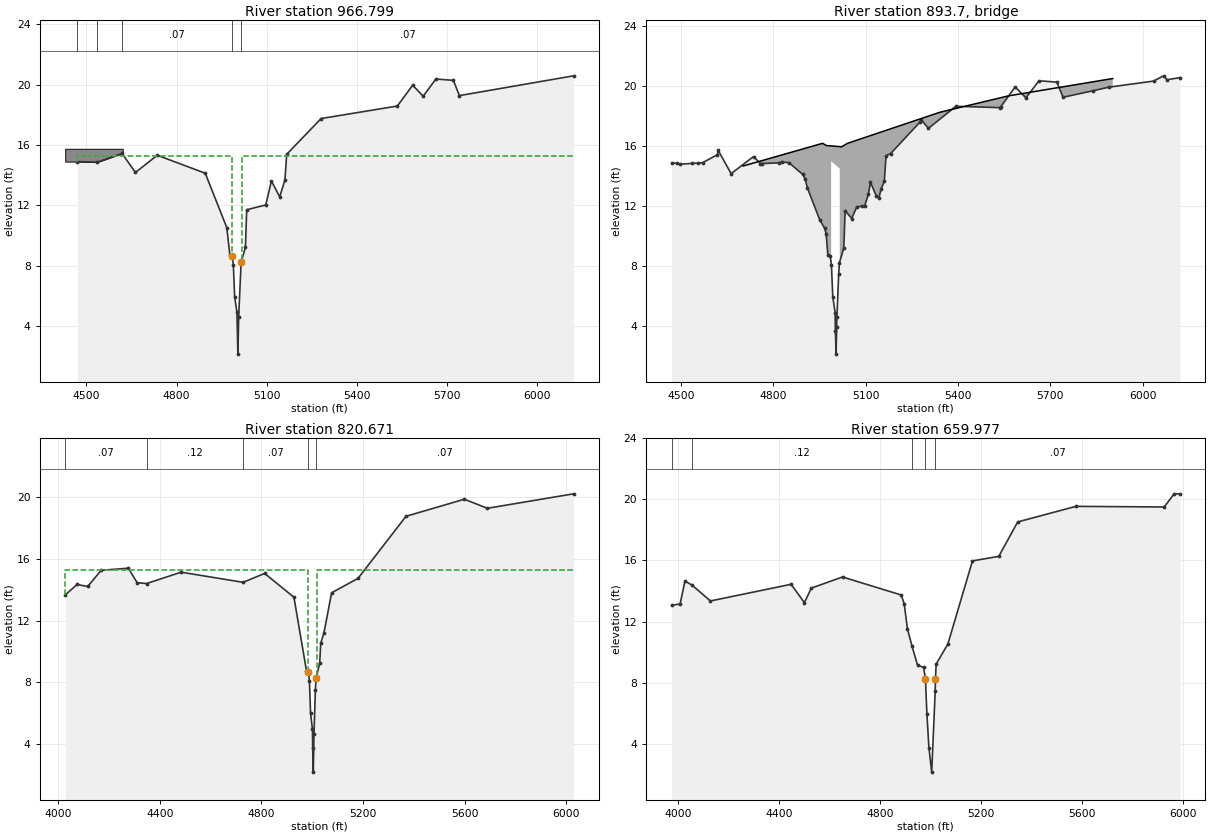
Type RM Length L Ch R = 1 ,966.799 ,133.62,146.13,151.33
XS GIS Cut Line= 4
     3202186.675    13797068.126     3202159.698    13796552.889
     3202149.031    13796525.105     3202212.132     13795421.13
#Sta/Elev= 30
 4469.88    14.9 4535.94   14.86 4618.51   15.44 4663.12   14.18  4735.8   15.32
 4895.48   14.13 4967.15   10.53  4977.3    8.73 4985.12    8.66 4988.95    8.08
 4993.34    5.96 5000.92    4.92 5004.11    2.15 5006.82    4.64 5014.88    8.24
 5029.21    9.22 5033.42   11.71 5096.91   12.03  5115.7   13.61 5143.33   12.57
 5160.77   13.68 5166.53   15.38 5280.97   17.75 5534.95   18.58 5585.86   19.96
 5620.88   19.23 5663.14   20.37 5721.49   20.28 5741.38   19.27 6121.36   20.58
#Mann= 5 ,-1 , 0
 4469.88     .07       0 4535.94     .12       0 4618.51     .07       0
 4985.12    .032       0 5014.88     .07       0
#XS Ineff= 2 , 0
       0 4985.12    15.3    5017       0    15.3
Permanent Ineff=
       F       F
#Block Obstruct= 1 ,-1
 4429.31  4620.7   15.75
Bank Sta=4985.12,5014.88
XS Rating Curve= 0
Exp/Cntr=.5,.3

Type RM Length L Ch R = 3 ,893.7   ,,,
BEGIN DESCRIPTION:
concrete bridge
END DESCRIPTION:
Bridge Culvert--1,0,-1,-1, 0
Deck Dist Width WeirC Skew NumUp NumDn MinLoCord MaxHiCord MaxSubmerge Is_Ogee
87,15,2.6,0, 12, 12, , , .95, 0, 0,0,,
    4702    4960    4973 4987.99    4988    5016 5016.01    5022    5041    5341
    5563    5903
   14.69    16.2   16.05   16.03   16.03   15.98   15.98   15.97    16.2   18.27
   19.36   20.52
                               0   15.01   14.51       0
                
    4702    4960    4973 4987.99    4988    5016 5016.01    5022    5041    5341
    5563    5903
   14.69    16.2   16.05   16.03   16.03   15.98   15.98   15.97    16.2   18.27
   19.36   20.52
                               0   15.01   14.51       0
                
Pier Skew, UpSta & Num, DnSta & Num=  ,4988.6, 2 ,4988.6, 2 , 0 , 0 , 0 ,,
       1       1
       0
       1       1
       0
Pier Skew, UpSta & Num, DnSta & Num=  ,4990, 2 ,4990, 2 , 0 , 0 , 0 ,,
     .67     .67
       0
     .67     .67
       0
Pier Skew, UpSta & Num, DnSta & Num=  ,5001, 2 ,5001, 2 , 0 , 0 , 0 ,,
       1       1
       0
       1       1
       0
Pier Skew, UpSta & Num, DnSta & Num=  ,5010, 2 ,5010, 2 , 0 , 0 , 0 ,,
     .67     .67
       0
     .67     .67
       0
Pier Skew, UpSta & Num, DnSta & Num=  ,5015.4, 2 ,5015.4, 2 , 0 , 0 , 0 ,,
       1       1
       0
       1       1
       0
BR Coef=-1 , 1 , 1 ,1.25, 0 ,,,.8,0,1.2,0,
WSPro=,,,, 1 ,,,, 0 ,,,, 0 ,,,,-1 ,-1 ,-1 , 0 , 0 , 0 , 0 , 0
BR U #Sta/Elev= 63
 4469.88    14.9 4488.33   14.86 4497.89   14.81 4535.94   14.86 4553.88   14.88
 4570.28   14.91 4618.51   15.44 4620.69   15.74 4663.12   14.18  4735.8   15.32
 4758.46   14.85 4763.42   14.85  4817.3    14.9 4828.34   14.95 4850.78   14.91
 4895.48   14.13    4903   13.85    4911   13.22    4951   11.09 4967.15   10.53
 4971.84   10.15  4977.3    8.73 4985.12    8.66 4988.95    8.08 4993.34    5.96
 5000.92    4.92 5001.63    3.72 5004.11    2.15 5005.83    3.93 5006.82    4.64
 5012.44    7.47 5014.88    8.24 5029.21    9.22 5033.42   11.71 5054.92   11.19
 5070.63   11.94 5086.78   12.02 5096.91   12.03 5108.89   12.79  5115.7   13.61
 5135.12   12.66 5143.33   12.57  5150.2   13.14 5160.77   13.68 5166.53   15.38
 5181.36   15.52 5276.79   17.62 5280.97   17.75 5304.24    17.2 5393.22   18.67
 5534.95   18.58 5539.14   18.64 5585.86   19.96 5620.88   19.23 5663.14   20.37
 5721.49   20.28 5741.38   19.27 5838.01    19.7 5889.43   19.94 6035.42   20.35
 6068.28    20.7 6079.13   20.44 6121.36   20.58
BR U #Mann= 5
 4469.88     .07 4535.94     .12 4618.51     .07 4985.12    .032 5014.88     .07
BR D #Sta/Elev= 64
 4027.33   13.66 4028.25   13.66 4073.88   14.34 4093.36   14.19 4115.77   14.21
 4168.95   15.26 4226.24    15.1 4275.81    15.4 4310.57   14.46 4347.55    14.4
 4350.66   14.39 4428.82   14.73 4470.22   15.03 4483.73   15.14 4604.66   14.78
 4695.87   14.53 4727.82   14.48  4752.7   14.44 4812.51   15.06 4825.53   14.94
 4886.87   13.92 4901.54   13.89 4927.94   13.51    4933   13.28    4941   12.09
    4958    10.4 4967.15    9.96 4971.84    9.46  4977.3    8.73 4985.12    8.66
 4988.95    8.08 4993.34    5.96 5000.92    4.92 5001.63    3.72 5004.11    2.15
 5005.83    3.93 5006.82    4.64 5012.44    7.47 5014.88    8.24 5029.21    9.22
 5033.42   10.53    5046   11.19 5059.92   12.46 5061.77   12.63 5062.54   12.61
 5076.18    13.8 5086.99   13.74  5180.4   14.74 5181.22   14.76 5181.69   14.77
 5181.92   14.77 5182.04   14.77 5245.51   16.31 5369.12   18.77  5419.9   19.03
 5520.53   19.54 5553.29   19.67 5598.91   19.88 5689.25   19.29 5857.95   19.68
 5863.23   19.68 5864.22    19.7 5889.93   19.72 6028.73   20.23
BR D #Mann= 5
 4027.33     .07 4347.55     .12 4727.82     .07 4985.12    .032 5014.88     .07
BC Design=,, 0 ,, 0 ,,,,,,
BC HTab HWMax=20.7

Type RM Length L Ch R = 1 ,820.671 ,160.81,160.69,158.84
XS GIS Cut Line= 3
     3202263.082    13797488.254     3202294.954    13796476.676
     3202408.654    13795493.916
#Sta/Elev= 30
 4027.33   13.66 4073.88   14.34 4115.77   14.21 4168.95   15.26 4275.81    15.4
 4310.57   14.46 4347.55    14.4 4483.73   15.14 4727.82   14.48 4812.51   15.06
 4927.94   13.51  4977.3    8.73 4985.12    8.66 4988.95    8.08 4993.34    5.96
 5000.92    4.92 5001.63    3.72 5004.11    2.15 5006.82    4.64 5012.44    7.47
 5014.88    8.24 5029.21    9.22 5033.42   10.53    5046   11.19 5076.18    13.8
  5180.4   14.74 5369.12   18.77 5598.91   19.88 5689.25   19.29 6028.73   20.23
#Mann= 5 ,-1 , 0
 4027.33     .07       0 4347.55     .12       0 4727.82     .07       0
 4985.12    .032       0 5014.88     .07       0
#XS Ineff= 2 , 0
       0 4985.12    15.3    5017       0    15.3
Permanent Ineff=
       F       F
Bank Sta=4985.12,5014.88
XS Rating Curve= 0
Exp/Cntr=.5,.3

Type RM Length L Ch R = 1 ,659.977 ,666.38,659.98,648.74
XS GIS Cut Line= 3
     3202423.211    13797531.925     3202455.002    13796485.385
      3202532.39     13795523.03
#Sta/Elev= 30
 3974.64   13.08 4007.92   13.14 4027.11   14.65 4055.14   14.39 4128.06   13.35
  4447.4   14.44 4500.15   13.24 4527.56   14.19    4651   14.92 4883.38   13.74
 4895.17   13.17    4908   11.53    4926    10.4    4948    9.15 4971.84       9
  4979.3    8.27  4985.1    5.96  4993.2    3.72 5004.11    2.15    5018    7.47
    5019    8.24  5021.7    9.22  5068.1   10.53 5165.48   15.97 5269.73   16.27
 5344.51   18.52  5575.2   19.54 5924.56    19.5 5963.32   20.35 5987.12   20.36
#Mann= 5 ,-1 , 0
 3974.64     .07       0 4055.14     .12       0    4926     .07       0
  4979.3    .032       0    5019     .07       0
Bank Sta=4979.3,5019
XS Rating Curve= 0
Exp/Cntr=.3,.1

Chan Stop Cuts=-1